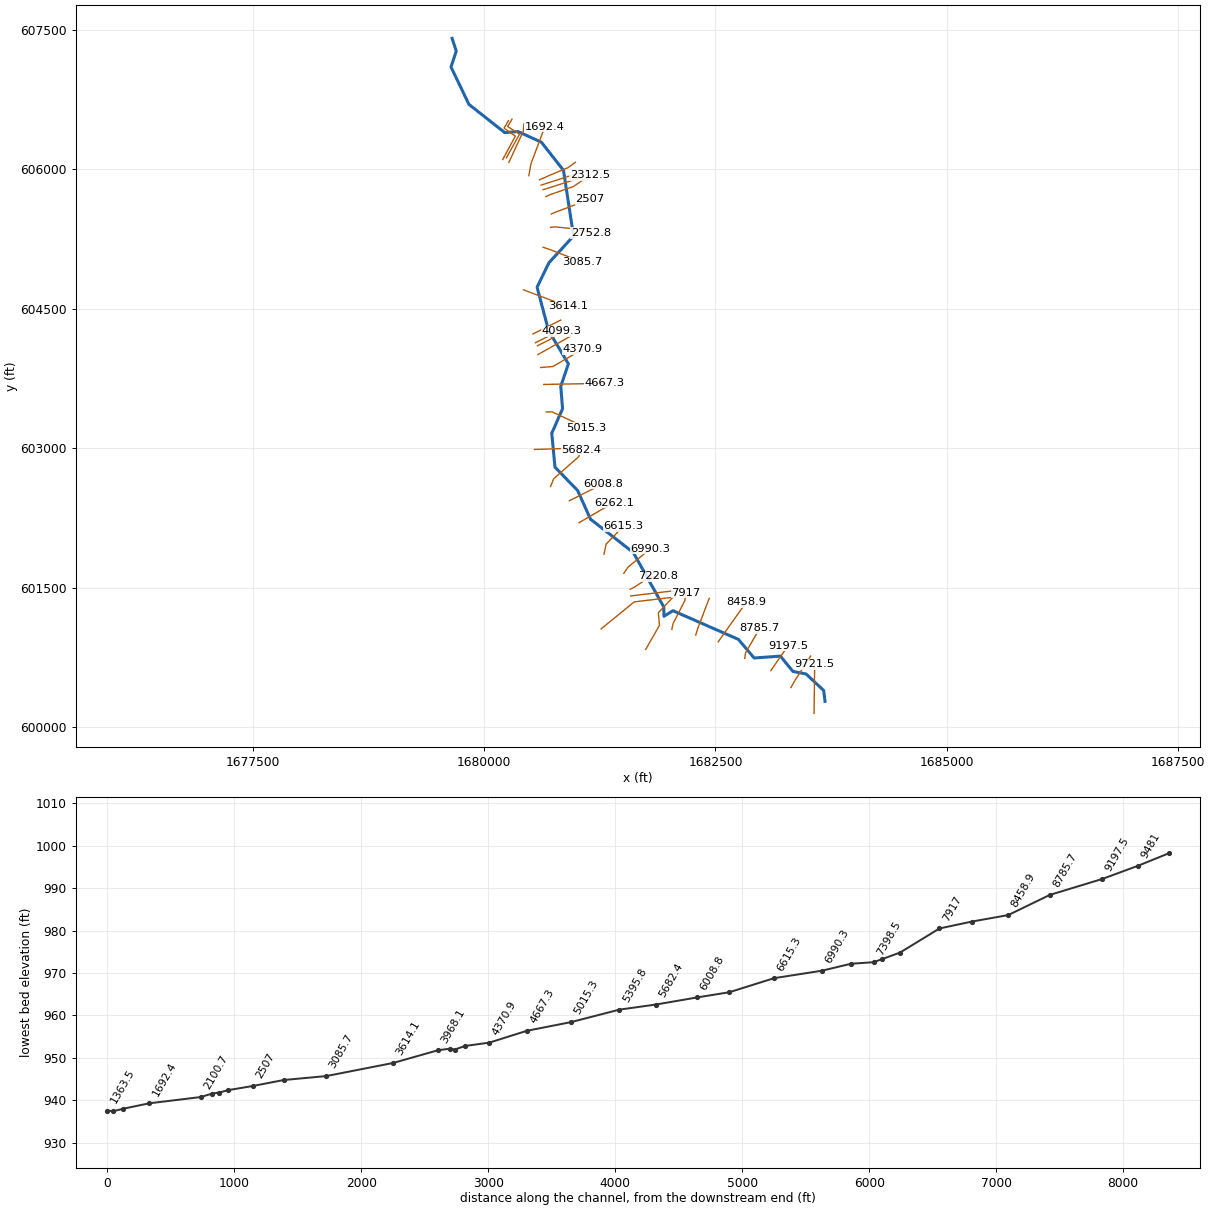
--- CSTLMNRN.prj (project) ---

Proj Title=CSTLMNRN
Current Plan=p01
Default Exp/Contr=0,0
English Units
Geom File=g01
Flow File=f01
Plan File=p01
BEGIN DESCRIPTION:
END DESCRIPTION:
DSS Export Rating Curves= 0
DSS Export Rating Curve Sorted= 0
DSS Export Volume Flow Curves= 0
DXF Filename=..\..\..\..\Engineering\Ohio\Hydraulics\CSTLMNRN\CSTLMNRN.
DXF OffsetX= 0
DXF OffsetY= 0
DXF ScaleX= 0
DXF ScaleY= 0

--- CSTLMNRN.p01 (plan) ---

Plan Title=Floodplain
Program Version=4.00
Geom File=g01
Flow File=f01
K Sum by GR=0
Std Step Tol=0.01
Critical Tol=0.01
Num of Std Step Trials=20
Max Error Tol=0.3
Flow Tol Ratio=0.001
Split Flow NTrial=30
Split Flow Tol=0.02
Split Flow Ratio=0.02
Log Output Level=0
Friction Slope Method=1
Unsteady Friction Slope Method=2
Unsteady Bridges Friction Slope Method=1
Global Log Level=0
CheckData=False
Run HTab=0
Run UNet=0
Run PostProcess=0
UNET Theta=0
UNET Theta Warmup=0
UNET ZTol=0
UNET ZSATol=0
UNET MxIter=0
UNET MaxInSteps=0
UNET DtIC=0
UNET DtMin=0
UNET MaxCRTS=0
UNET WFStab=0
UNET SFStab=0
UNET WFX=0
UNET SFX=0
UNET DSS MLevel=0
UNET DZMax Abort=0
UNET Convert EG Bridges=0
UNET Use Existing IB Tables=0
UNET Froude Limit=0
UNET Froude Power=0
Write IC File=0
Echo Input=False
Echo Output=False
Write Detailed=0

--- CSTLMNRN.f01 (steady flow) ---

Flow Title=NFF Regression Equation
Program Version=4.10
Number of Profiles= 1
Profile Names=P100yr
River Rch & RM=CSTLMNRN,Main            ,9721.5
  971.71
River Rch & RM=CSTLMNRN,Main            ,8172.4
1197.052
River Rch & RM=CSTLMNRN,Main            ,7467.1
  1953.7
River Rch & RM=CSTLMNRN,Main            ,4667.3
2126.794
River Rch & RM=CSTLMNRN,Main            ,475
2127.817
Boundary for River Rch & Prof#=CSTLMNRN,Main            , 1
Up Type= 0
Dn Type= 1
Dn Known WS=939.76
DSS Import GetInterval= 0
DSS Import GetPeak= 0
DSS Import FillOption= 0

--- CSTLMNRN.g01 (geometry) ---

Geom Title=USGS 10m DEM
Program Version=4.10

River Reach=CSTLMNRN        ,Main
Reach XY= 30
     1683683.504       600278.08     1683668.929      600395.623
     1683479.077      600572.351     1683337.303      600599.228
     1683201.886      600764.159     1682918.058      600744.256
     1682748.183      600944.078     1682040.547      601252.973
     1681943.495      601192.342     1681942.049      601292.304
     1681611.957      601878.947     1681150.093      602237.481
     1681011.211      602545.501     1680766.412      602796.509
      1680731.69      603161.092     1680848.385      603425.457
     1680828.912      603665.432     1680911.059      603907.575
     1680696.968      604265.258     1680572.836      604732.272
     1680701.308      604995.293     1680966.933      605282.619
     1680858.426      605988.349     1680619.711        606291.3
     1680365.785      606406.507     1680223.814      606394.528
     1679836.725      606698.418     1679643.148      607100.328
     1679699.572      607270.467     1679655.072      607408.556

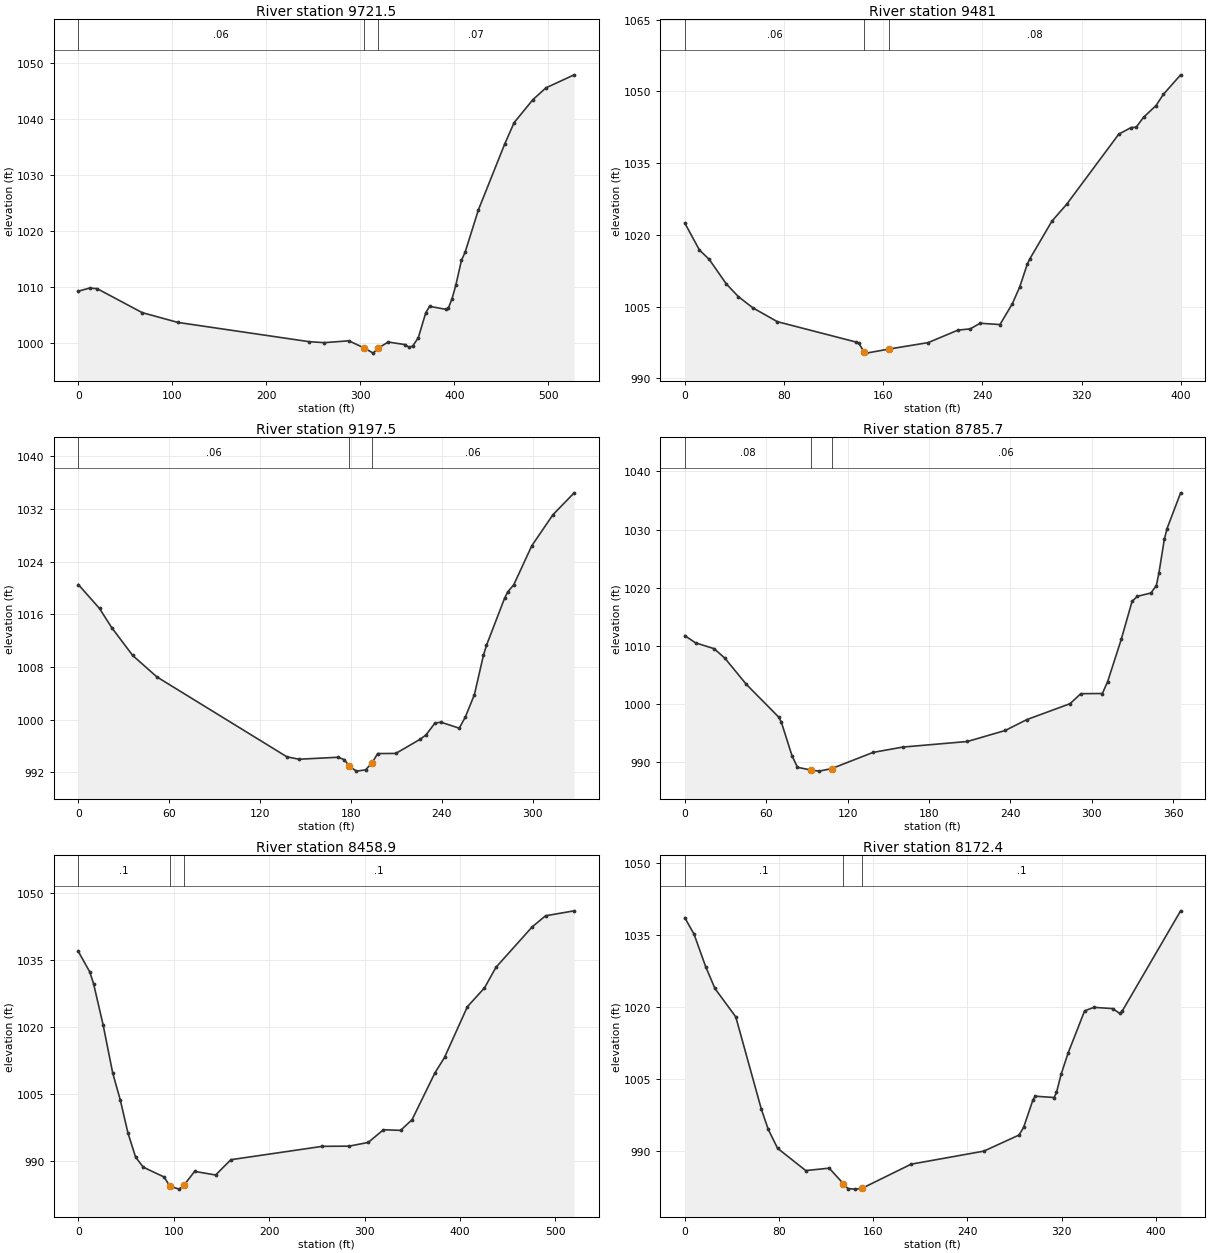
Type RM Length L Ch R = 1 ,9721.5  ,252.3,240.5,223.4
XS GIS Cut Line= 2
     1683565.332      600148.568     1683571.843      600675.911
#Sta/Elev= 30
       0 1009.28      12 1009.83      20 1009.73    67.9 1005.45   105.9  1003.7
   245.7 1000.26   261.7 1000.09   287.7 1000.42     304  999.15   313.6  998.22
     319  999.11   329.6  1000.2   347.6  999.74   351.6  999.29   355.6  999.47
   361.6 1000.96   369.6 1005.44   373.6 1006.57   391.5 1006.02   393.5 1006.22
   397.5 1007.93   401.5 1010.32   407.5 1014.77   411.5 1016.27   425.5 1023.77
   453.5 1035.53   463.5 1039.35   483.4 1043.44   497.4 1045.57   527.4 1047.89
#Mann= 3 , 0 , 0
       0     .06       0     304    .045       0     319     .07       0
Bank Sta=304,319
XS Rating Curve= 0 ,0
Exp/Cntr=0.3,0.1

Type RM Length L Ch R = 1 ,9481    ,284,283.5,285.2
XS GIS Cut Line= 3
     1683315.767      600426.346     1683356.999       600500.13
      1683528.44      600764.887
#Sta/Elev= 30
       0 1022.49    11.8 1016.85    19.7  1014.9    33.4 1009.79    43.2 1007.11
      55 1004.75    74.7 1001.87   138.4   997.6   140.4  997.36   144.4  995.62
   146.4   995.3   164.4  996.14   196.3   997.5   220.3 1000.11   230.2 1000.37
   238.2 1001.55   254.2 1001.27   264.2 1005.64   270.2 1009.19   276.2 1013.88
   278.2 1014.97   296.1 1022.89   308.1 1026.45     350 1041.07     360 1042.46
     364  1042.5     370  1044.6     380 1047.03     386 1049.39   399.9 1053.47
#Mann= 3 , 0 , 0
       0     .06       0   144.4    .045       0   164.4     .08       0
Bank Sta=144.4,164.4
XS Rating Curve= 0 ,0
Exp/Cntr=0.3,0.1

Type RM Length L Ch R = 1 ,9197.5  ,409.8,411.7,412.7
XS GIS Cut Line= 2
     1683098.753      600608.637     1683285.385      600877.734
#Sta/Elev= 30
       0 1020.53      14 1016.89      22    1014    35.9 1009.75    51.9 1006.49
   137.8  994.34   145.8  993.98   171.7  994.28   175.7   993.9   179.1   992.9
   183.7  992.17   189.7  992.36   194.1  993.45   197.7  994.84   209.7  994.86
   225.6  996.99   229.6  997.66   235.6  999.49   239.6   999.6   251.6   998.7
   255.6 1000.38   261.6 1003.79   267.6  1009.8   269.6  1011.3   281.6 1018.48
   283.6 1019.41   287.6 1020.49   299.5 1026.42   313.5 1031.15   327.5 1034.47
#Mann= 3 , 0 , 0
       0     .06       0   179.1    .045       0   194.1     .06       0
Bank Sta=179.1,194.1
XS Rating Curve= 0 ,0
Exp/Cntr=0.3,0.1

Type RM Length L Ch R = 1 ,8785.7  ,327.7,326.9,324.1
XS GIS Cut Line= 3
     1682816.635      600741.016     1682825.315      600799.609
     1682979.395      601064.366
#Sta/Elev= 30
       0 1011.74     7.9  1010.5    21.7 1009.49    29.6 1007.85    45.4 1003.35
    69.2  997.73    71.2  996.84    79.1  991.03    83.1  989.08      93  988.61
      99  988.42   108.2  988.85   138.8  991.64   160.7  992.56   208.4  993.52
   236.3  995.42   252.2  997.29     284 1000.02     292 1001.75   307.9 1001.78
   311.8 1003.84   321.8 1011.08   329.8 1017.64   333.7 1018.51   343.7 1019.08
   347.7 1020.36   349.6 1022.52   353.6 1028.34   355.6 1030.18   365.6 1036.32
#Mann= 3 , 0 , 0
       0     .08       0      93    .045       0   108.2     .06       0
Bank Sta=93,108.2
XS Rating Curve= 0 ,0
Exp/Cntr=0.3,0.1

Type RM Length L Ch R = 1 ,8458.9  ,280.3,286.5,291.8
XS GIS Cut Line= 2
     1682530.176      600918.967     1682831.826      601342.144
#Sta/Elev= 30
       0 1036.98      12 1032.38      16 1029.72      26 1020.49      36 1009.75
      44 1003.64      52  996.28      60  990.87      68   988.6      90  986.38
      96  984.29   105.9  983.67     111  984.64   121.9  987.65   143.9  986.84
   159.9  990.27   255.8  993.27   283.8  993.31   303.8  994.14   319.8  996.99
   337.8  996.85   349.8  999.25   373.8 1009.76   383.8  1013.2   407.8 1024.59
   425.7  1028.8   437.7 1033.41   475.7 1042.49   489.7 1044.98   519.7 1046.09
#Mann= 3 , 0 , 0
       0      .1       0      96    .045       0     111      .1       0
Bank Sta=96,111
XS Rating Curve= 0 ,0
Exp/Cntr=0.3,0.1

Type RM Length L Ch R = 1 ,8172.4  ,257.4,255.5,252.3
XS GIS Cut Line= 3
     1682287.121      600990.582     1682308.822      601062.196
      1682432.52      601385.547
#Sta/Elev= 30
       0 1038.58     7.9 1035.13    17.7 1028.42    25.6 1023.86    43.3 1017.95
      65  998.76    70.9  994.54    78.8  990.63   102.7     986   122.6   986.5
   134.7  983.25   138.5  982.26   144.5  982.14   150.4   982.3   192.2  987.33
   253.9  990.04   283.8  993.39   287.7  994.99   295.7 1000.77   297.7 1001.46
   313.6 1001.19   315.6 1002.24   319.6 1006.08   325.5 1010.46   339.5 1019.22
   347.4 1019.94   363.3 1019.68   369.3 1018.68   371.3 1019.12     421 1040.01
#Mann= 3 , 0 , 0
       0      .1       0   134.7    .045       0   150.4      .1       0
Bank Sta=134.7,150.4
XS Rating Curve= 0 ,0
Exp/Cntr=0.3,0.1

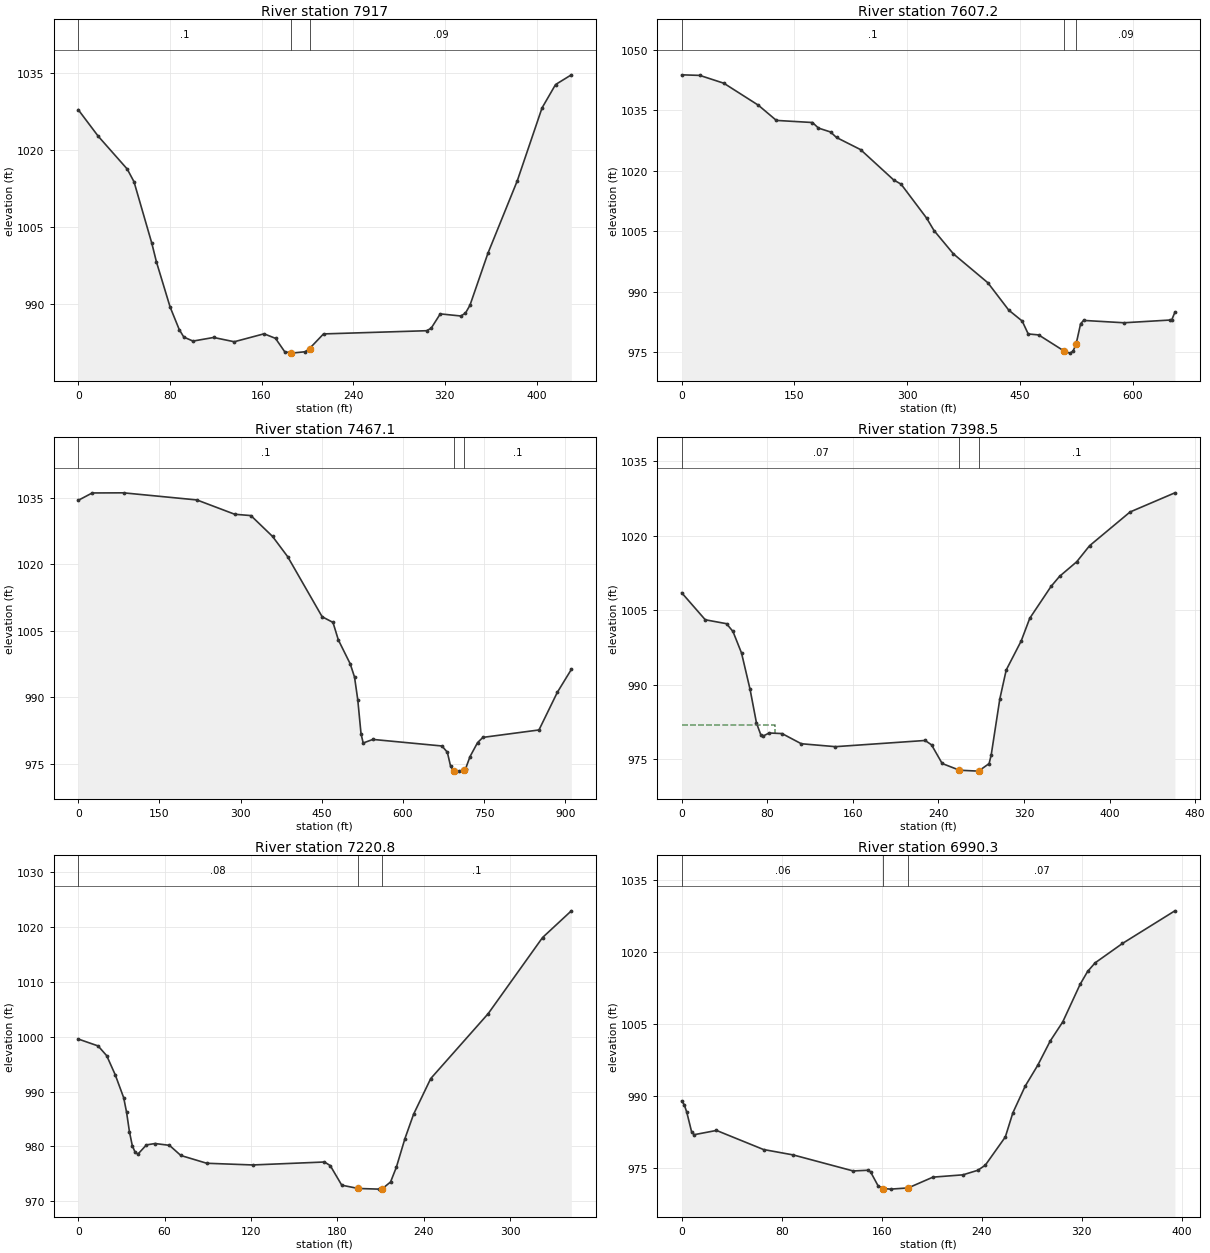
Type RM Length L Ch R = 1 ,7917    ,315.3,309.8,302.2
XS GIS Cut Line= 4
     1682028.874      601051.346     1682041.895       601114.28
     1682167.763      601357.335     1682182.954      601448.481
#Sta/Elev= 30
       0 1027.79    17.5 1022.62    42.8 1016.25    48.7 1013.79    64.3  1001.8
    68.3  998.21    80.2  989.47    88.2  985.08    92.2  983.62   100.2  982.85
   118.2  983.55   136.2  982.72   162.2  984.26   172.2  983.38   180.2  980.79
   186.1  980.51   198.1  980.78   201.9   981.4   214.1  984.24     304  984.86
     308  985.33     316  988.13     334  987.72     338  988.29   341.9   989.8
   357.6  999.91   383.2 1013.97   404.8 1028.12   416.6 1032.66   430.4 1034.55
#Mann= 3 , 0 , 0
       0      .1       0   186.1    .045       0   201.9     .09       0
Bank Sta=186.1,201.9
XS Rating Curve= 0 ,0
Exp/Cntr=0.3,0.1

Type RM Length L Ch R = 1 ,7607.2  ,145.7,140.1,123.2
XS GIS Cut Line= 4
     1681746.756      600836.502     1681895.024      601094.807
     1681883.475      601231.467     1682035.385      601392.057
#Sta/Elev= 30
       0 1043.75      24 1043.61      56 1041.67   101.9 1036.23   125.9 1032.46
   173.9 1031.94   181.9 1030.56   197.9  1029.6   205.9 1028.23   237.9 1025.23
   281.8 1017.74   291.8 1016.67   325.7 1008.28   335.6 1005.19   361.4  999.41
   407.2  992.26     435  985.48   452.9  982.77   460.9  979.58   474.8  979.34
   508.7  975.34   516.6  974.83   520.6  975.35   524.6  977.07   530.6  982.11
   534.6  982.93   588.3  982.35   650.1  983.03     652  983.15     656  984.95
#Mann= 3 , 0 , 0
       0      .1       0   508.7    .045       0   524.6     .09       0
Bank Sta=508.7,524.6
XS Rating Curve= 0 ,0
Exp/Cntr=0.3,0.1

Type RM Length L Ch R = 1 ,7467.1  ,68.6,68.6,68.6
XS GIS Cut Line= 3
     1681264.985      601057.856     1681622.908      601347.752
     1682070.107      601400.738
#Sta/Elev= 30
       0 1034.46    25.9 1036.13    83.7 1036.16   219.3 1034.55   289.1 1031.32
     319 1031.02   358.9 1026.32   386.8 1021.76   450.6 1008.17   470.6 1006.89
   480.5 1002.94   502.4  997.54   510.4  994.55   516.4  989.41   522.4  981.75
   526.4  979.65   544.3  980.46   671.8  978.98   681.8  977.58   687.8  974.43
   693.7  973.33   703.7   973.3   711.7  973.52   715.6  973.86   723.6  976.55
   737.6  979.73   747.5  980.92   851.1   982.6     885   991.1   910.9  996.28
#Mann= 3 , 0 , 0
       0      .1       0   693.7    .045       0   711.7      .1       0
#XS Ineff= 2 , 0
          543.94  980.43
Permanent Ineff=
       F       F
Bank Sta=693.7,711.7
XS Rating Curve= 0 ,0
Exp/Cntr=0.3,0.1

Type RM Length L Ch R = 1 ,7398.5  ,167,177.7,187.8
XS GIS Cut Line= 2
     1681583.996      601411.589     1682041.895      601465.842
#Sta/Elev= 30
       0  1008.5      22 1003.06    41.9 1002.27    47.9  1000.7    55.9  996.37
    63.9  989.03    69.9  982.24    73.9  979.89    75.8  979.59    81.8  980.24
    93.8  980.12   111.8  978.07   143.7  977.48   227.6  978.73   233.6  977.84
   243.5  974.09   259.7  972.73   277.5  972.55   287.4  974.07   289.4  975.86
   297.4  987.09   303.4  992.94   317.4  998.79   325.4 1003.36   345.3 1009.78
   353.3 1011.82   369.3 1014.75   381.3 1017.98   419.2 1024.79   461.1 1028.65
#Mann= 3 , 0 , 0
       0     .07       0   259.7    .045       0   277.5      .1       0
#XS Ineff= 2 , 0
           87.59  981.88
Permanent Ineff=
       F       F
Bank Sta=259.7,277.5
XS Rating Curve= 0 ,0
Exp/Cntr=0.3,0.1

Type RM Length L Ch R = 1 ,7220.8  ,227.5,230.5,233.6
XS GIS Cut Line= 4
     1681577.485      601483.203     1681625.228      601507.075
     1681779.308      601606.901     1681883.475      601624.262
#Sta/Elev= 30
       0  999.58    13.8  998.32    19.8  996.54    25.7  993.07    31.6  988.87
    33.6  986.22    35.6  982.66    37.6   980.1    39.5  978.95    41.5  978.58
    47.4  980.26    53.4  980.51    63.4  980.18    71.3  978.33    89.3  976.91
   121.2   976.6   171.1  977.14   175.1  976.48   183.1  972.91   194.5  972.31
     209  972.19     211   972.2     217   973.5     221  976.16     227  981.42
     233  985.86   244.9  992.36   284.8  1004.2   322.6  1018.1   342.6 1022.97
#Mann= 3 , 0 , 0
       0     .08       0   194.5    .045       0     211      .1       0
Bank Sta=194.5,211
XS Rating Curve= 0 ,0
Exp/Cntr=0.3,0.1

Type RM Length L Ch R = 1 ,6990.3  ,371.4,375,376
XS GIS Cut Line= 3
     1681510.211      601654.644     1681555.784      601721.918
     1681798.839      601919.401
#Sta/Elev= 30
       0  988.92       2  988.15       4  986.61     7.9  982.49     9.9  981.89
    27.8  982.78    65.4   978.8    89.2  977.67   137.1  974.33   149.1  974.48
   151.1   974.1   157.1   971.2     161  970.67     167  970.54   181.1  970.79
   200.9  973.04   224.9  973.52   236.8  974.47   242.8  975.54   258.8  981.42
   264.8  986.44   274.7  992.03   284.7  996.36   294.7 1001.43   304.7 1005.41
   318.6 1013.25   324.6 1015.94   330.6 1017.73   352.5 1021.78   394.4 1028.58
#Mann= 3 , 0 , 0
       0     .06       0     161    .045       0   181.1     .07       0
Bank Sta=161,181.1
XS Rating Curve= 0 ,0
Exp/Cntr=0.3,0.1

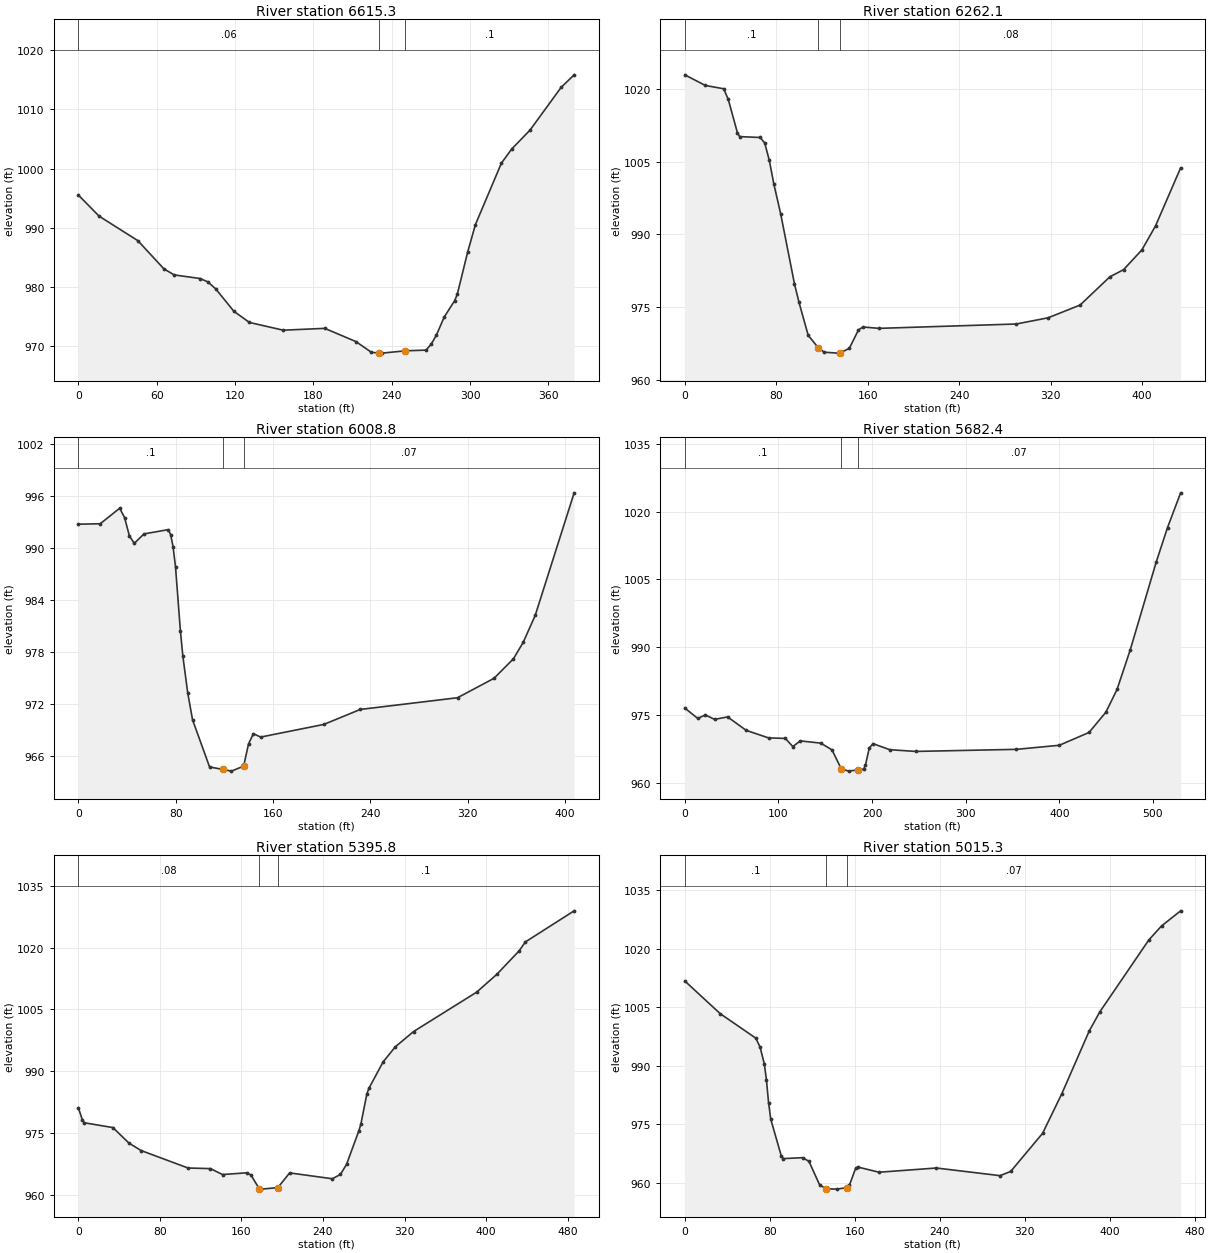
Type RM Length L Ch R = 1 ,6615.3  ,358.5,353.2,346
XS GIS Cut Line= 3
     1681295.367      601860.807     1681319.239      601969.314
     1681505.871      602162.457
#Sta/Elev= 30
       0  995.53    15.9  991.96    45.6  987.81    65.5  983.05    73.4  982.02
    93.2  981.41    99.2  980.84   105.2  979.66   119.1  975.87     131  973.98
   156.9  972.67   188.7  972.98   212.6  970.74   224.5  968.92   230.5  968.81
   232.5  968.79   250.4  969.18   266.3   969.3   270.3  970.33   274.2  971.83
   280.2   974.9   288.2  977.66   290.2  978.74   298.1  985.85   304.1  990.54
     324 1000.93   331.9 1003.32   345.9 1006.51   369.7 1013.73   379.7 1015.86
#Mann= 3 , 0 , 0
       0     .06       0   230.5    .045       0   250.4      .1       0
Bank Sta=230.5,250.4
XS Rating Curve= 0 ,0
Exp/Cntr=0.3,0.1

Type RM Length L Ch R = 1 ,6262.1  ,254.3,253.4,251.6
XS GIS Cut Line= 2
      1681026.27      602199.349     1681401.704      602416.363
#Sta/Elev= 30
       0 1022.99      18 1020.79      34 1020.11      38 1017.92      46 1011.03
      48 1010.22      66 1010.04    69.9 1008.89    73.9 1005.31    77.9 1000.38
    83.9   994.2    95.9  979.79    99.9  975.94   107.9  969.16   116.6  966.62
   121.9  965.66   133.9  965.47   135.9  965.51   143.9  966.47   151.9  970.28
   155.9  970.87   169.9  970.59   289.8  971.49   317.7  972.77   345.7  975.41
   371.7  981.24   383.7  982.72   399.7   986.8   411.7  991.79   433.6 1003.76
#Mann= 3 , 0 , 0
       0      .1       0   116.6    .045       0   135.9     .08       0
Bank Sta=116.6,135.9
XS Rating Curve= 0 ,0
Exp/Cntr=0.3,0.1

Type RM Length L Ch R = 1 ,6008.8  ,320.3,326.4,332.1
XS GIS Cut Line= 2
     1680922.103      602435.894     1681286.687      602618.186
#Sta/Elev= 30
       0  992.74      18  992.79      34  994.58      38  993.51      42  991.38
      46  990.53      54  991.62    73.9  992.11    75.9  991.54    77.9  990.13
    79.9   987.8    83.9  980.44    85.9  977.54    89.9  973.29    93.9  970.16
   107.9  964.72   119.1  964.43   125.9  964.24   135.9  964.82   139.9  967.38
   143.9  968.56   149.9  968.17   201.8  969.63   231.8  971.36   311.7  972.71
   341.7  974.95   357.7  977.21   365.7   979.1   375.6  982.22   407.6  996.36
#Mann= 3 , 0 , 0
       0      .1       0   119.1    .045       0   135.9     .07       0
Bank Sta=119.1,135.9
XS Rating Curve= 0 ,0
Exp/Cntr=0.3,0.1

Type RM Length L Ch R = 1 ,5682.4  ,301.7,286.6,270.5
XS GIS Cut Line= 4
      1680718.11      602587.804     1680752.832      602672.439
      1681021.93      602908.984     1681052.312      602982.769
#Sta/Elev= 30
       0  976.52    13.9  974.21    21.9     975    31.8  974.01    45.7  974.56
    65.6  971.58    89.5  969.91   107.4   969.8   115.4  967.99   123.3  969.25
   145.2  968.76   157.2  967.27   167.1  963.08   175.1  962.56   184.6  962.84
     191  962.99     193  963.94     197  967.64     201  968.64   218.9   967.3
   246.7  966.92   354.2  967.38     400  968.28   431.8  971.12   449.8  975.61
   461.7  980.64   475.7  989.34   503.6 1008.87   515.6 1016.45   529.6 1024.14
#Mann= 3 , 0 , 0
       0      .1       0   167.1    .045       0   184.6     .07       0
Bank Sta=167.1,184.6
XS Rating Curve= 0 ,0
Exp/Cntr=0.3,0.1

Type RM Length L Ch R = 1 ,5395.8  ,390.1,380.5,369.1
XS GIS Cut Line= 2
     1680544.499      602987.109      1681030.61        603002.3
#Sta/Elev= 30
       0  981.13       4  978.15       6  977.47    33.9  976.31    49.8  972.51
    61.8  970.71   107.6  966.49   129.6  966.34   141.5   964.9   165.4  965.33
   169.4  964.77   177.4  961.47   179.4  961.36   195.7  961.72   207.3   965.3
   249.2  963.88   257.1  964.93   263.1  967.36   275.1  975.46   277.1  977.07
     283  984.42     285  985.82     299  992.26   310.9  995.91   328.9  999.64
   390.7 1009.19   410.6 1013.54   432.5 1019.25   438.5 1021.39   486.4 1028.95
#Mann= 3 , 0 , 0
       0     .08       0   177.4    .045       0   195.7      .1       0
Bank Sta=177.4,195.7
XS Rating Curve= 0 ,0
Exp/Cntr=0.3,0.1

Type RM Length L Ch R = 1 ,5015.3  ,337.1,348,358.1
XS GIS Cut Line= 3
     1680672.537      603390.755     1680735.471      603390.755
     1681102.225      603221.484
#Sta/Elev= 30
       0 1011.75    33.4 1003.36    66.9  997.09    70.9   994.8    74.9  990.48
    76.9  986.34    78.9  980.55    80.9  976.37    90.9  966.88    92.9  966.24
   110.9  966.48   116.9  965.55   126.9  959.54   132.9  958.52   142.9  958.42
   152.9   958.8   154.9  959.35   160.9  963.77   162.9  964.08   182.9  962.75
   236.9  963.83   296.9  961.87   306.9  962.96   336.9  972.71   354.9  982.79
   380.9  998.98   390.9 1003.87   436.9 1022.24   448.9 1025.84   466.9 1029.72
#Mann= 3 , 0 , 0
       0      .1       0   132.9    .045       0   152.9     .07       0
Bank Sta=132.9,152.9
XS Rating Curve= 0 ,0
Exp/Cntr=0.3,0.1

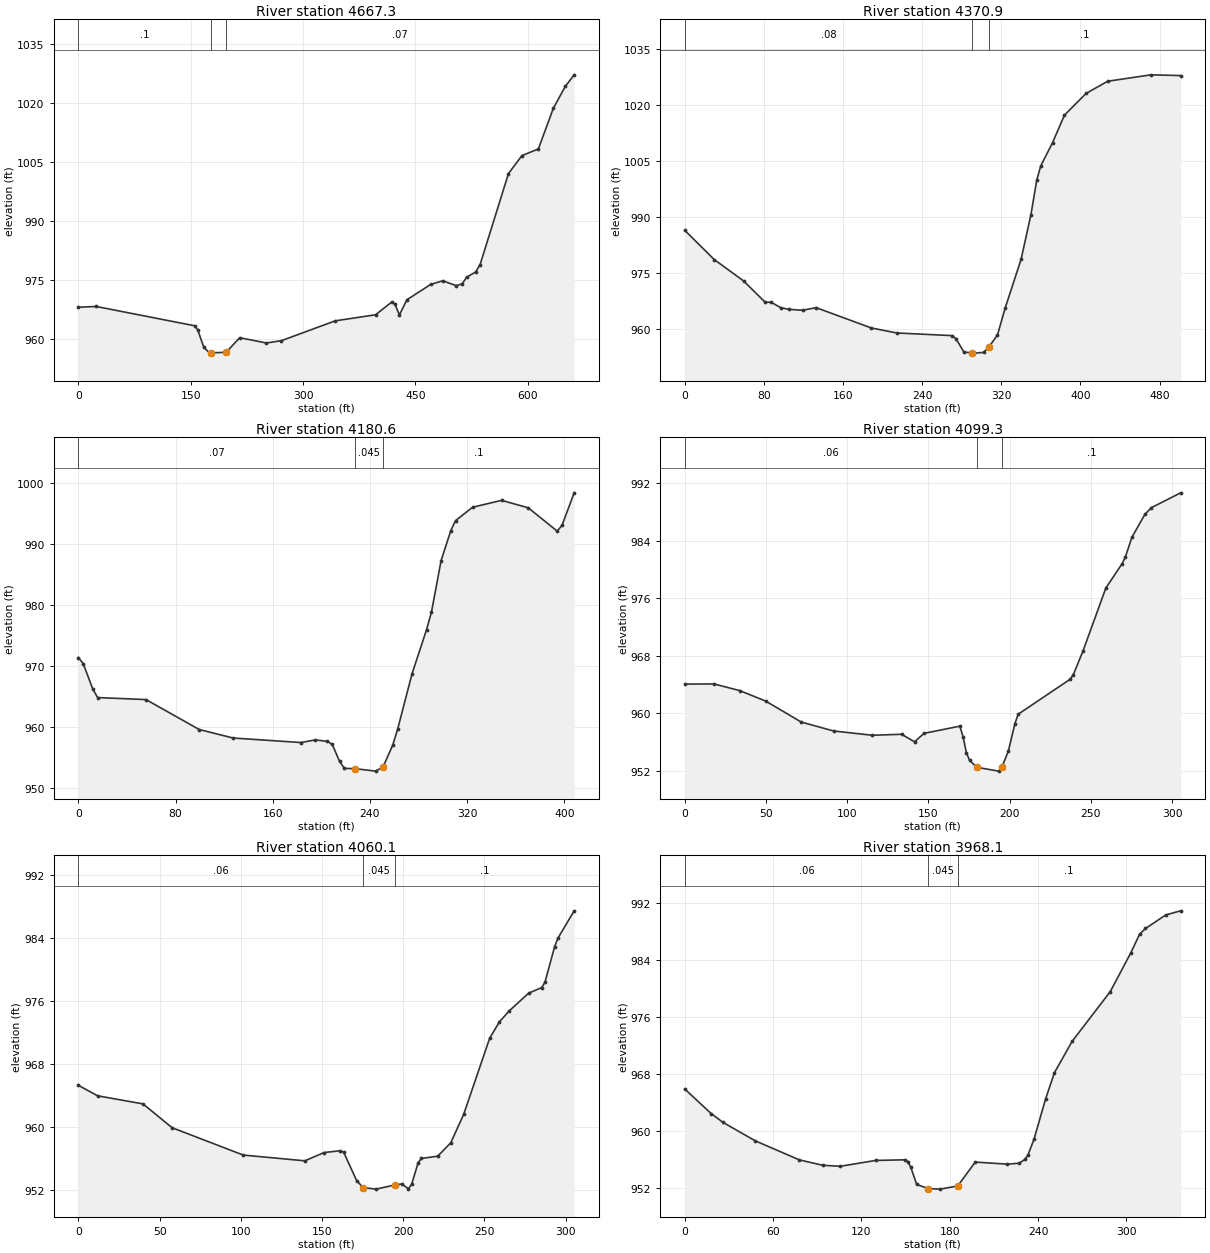
Type RM Length L Ch R = 1 ,4667.3  ,284,296.4,307.1
XS GIS Cut Line= 2
     1680644.326      603685.894     1681306.218      603698.915
#Sta/Elev= 30
       0  968.05    23.9  968.23   155.5  963.32   159.5  962.25   167.5  957.86
   175.5  956.37   177.5  956.42   197.4   956.6   215.4  960.29   251.2  958.95
   271.2  959.54     343  964.58   396.8  966.12   418.8  969.41   422.7  968.82
   428.7  966.08   438.7  969.94   470.6  973.86   486.6  974.76   504.5  973.53
   512.5     974   518.4  975.66   530.4     977   536.4  978.88   574.3 1002.03
   592.2 1006.59   614.2 1008.29   634.1 1018.58   650.1 1024.19     662 1027.14
#Mann= 3 , 0 , 0
       0      .1       0   177.5    .045       0   197.4     .07       0
Bank Sta=177.5,197.4
XS Rating Curve= 0 ,0
Exp/Cntr=0.3,0.1

Type RM Length L Ch R = 1 ,4370.9  ,190.4,190.3,189.7
XS GIS Cut Line= 3
     1680611.773      603868.186     1680744.152      603879.036
     1681063.162      604063.498
#Sta/Elev= 30
       0  986.47    29.7  978.66    59.5  972.91    81.3   967.2    87.2  967.22
    97.1  965.74   105.1  965.31     119  965.05   132.8  965.76   188.6  960.31
   214.5  958.97   270.3  958.26   274.2  957.44   282.2  953.85   290.2  953.65
   292.2  953.57   302.1  953.76   307.5  955.23   316.1  958.42     324  965.72
     340   978.7   349.9   990.6   355.9    1000   359.9 1003.76   371.8 1009.97
   383.8 1017.34   405.7 1023.17   427.6 1026.44   471.4 1028.16   501.3 1027.96
#Mann= 3 , 0 , 0
       0     .08       0   290.2    .045       0   307.5      .1       0
Bank Sta=290.2,307.5
XS Rating Curve= 0 ,0
Exp/Cntr=0.3,0.1

Type RM Length L Ch R = 1 ,4180.6  ,79.1,81.3,83.2
XS GIS Cut Line= 2
     1680581.392      604007.075     1680937.294      604206.727
#Sta/Elev= 30
       0  971.38       4   970.4    11.9  966.22    15.9  964.83    55.7   964.5
    99.5   959.6   127.4  958.21   183.1  957.47   195.1   957.9     205  957.66
     209  957.17     215  954.38     219  953.24   227.9  953.19   244.8  952.79
   250.8  953.47   258.8  957.06   262.8  959.64   274.7  968.75   286.6  975.94
   290.6  978.78   298.6  987.26   306.6  992.17   310.5  993.79   324.5  995.98
   348.4  997.11   370.3  995.89   394.1  992.08   398.1  993.01   408.1  998.34
#Mann= 3 , 0 , 0
       0     .07       0   227.9    .045       0   250.8      .1       0
Bank Sta=227.9,250.8
XS Rating Curve= 0 ,0
Exp/Cntr=0.3,0.1

Type RM Length L Ch R = 1 ,4099.3  ,39.1,39.1,39.1
XS GIS Cut Line= 3
     1680577.051      604102.561      1680715.94      604172.005
     1680839.638      604256.641
#Sta/Elev= 30
       0  964.06    17.9  964.09    33.8  963.16    49.8   961.7    71.7  958.78
    91.6  957.54   115.5  956.94   133.4  957.08   141.4  956.04   147.3  957.21
   169.3  958.21   171.3  956.72   173.3  954.54   175.3  953.44   179.8  952.48
   193.2  951.95   195.2  952.49   199.2  954.77   203.2  958.56   205.2  959.87
   237.2  964.74   239.2   965.4   245.2  968.73   259.2  977.45   269.2  980.83
   271.2  981.76   275.2   984.5   283.2  987.69   287.2  988.62   305.2  990.69
#Mann= 3 , 0 , 0
       0     .06       0   179.8    .045       0   195.2      .1       0
Bank Sta=179.8,195.2
XS Rating Curve= 0 ,0
Exp/Cntr=0.3,0.1

Type RM Length L Ch R = 1 ,4060.1  ,94.9,92,88.7
XS GIS Cut Line= 3
      1680555.35      604135.113     1680694.239      604204.557
     1680817.937      604289.193
#Sta/Elev= 30
       0  965.31    11.9  963.97    39.8  962.95    57.7  959.93   101.5  956.46
   139.4  955.73   151.3  956.78   161.3  957.01   163.3  956.83   171.3  953.23
   175.3  952.33   183.3  952.14   194.8  952.67   199.2  952.79   203.2  952.18
   205.2  952.78   209.2  955.51   211.2  956.03   221.2  956.32   229.2     958
   237.2  961.62   253.2  971.28   259.2  973.35   265.2  974.74   277.2  976.99
   285.2   977.7   287.2  978.36   293.2   982.9   295.2  983.96   305.2  987.43
#Mann= 3 , 0 , 0
       0     .06       0   175.3    .045       0   194.8      .1       0
Bank Sta=175.3,194.8
XS Rating Curve= 0 ,0
Exp/Cntr=0.3,0.1

Type RM Length L Ch R = 1 ,3968.1  ,375.3,354.1,330.2
XS GIS Cut Line= 3
     1680527.138      604228.429      1680557.52       604243.62
     1680828.787      604378.168
#Sta/Elev= 30
       0  965.85      18  962.39      26  961.16    47.9  958.57    77.8   955.9
    93.7  955.14   105.7     955   129.6  955.82   149.5  955.91   151.5  955.67
   153.5  954.88   157.5  952.45   165.4  951.87   173.4  951.79   185.4  952.23
   197.3  955.59   219.2   955.3   227.2  955.43   231.2  955.99   233.2  956.63
   237.2   958.8   245.1  964.47   251.1  968.16   263.1  972.55     289  979.54
   302.9  984.96   308.9  987.59   312.9  988.41   326.8  990.32   336.8  990.89
#Mann= 3 , 0 , 0
       0     .06       0   165.4    .045       0   185.4      .1       0
Bank Sta=165.4,185.4
XS Rating Curve= 0 ,0
Exp/Cntr=0.3,0.1

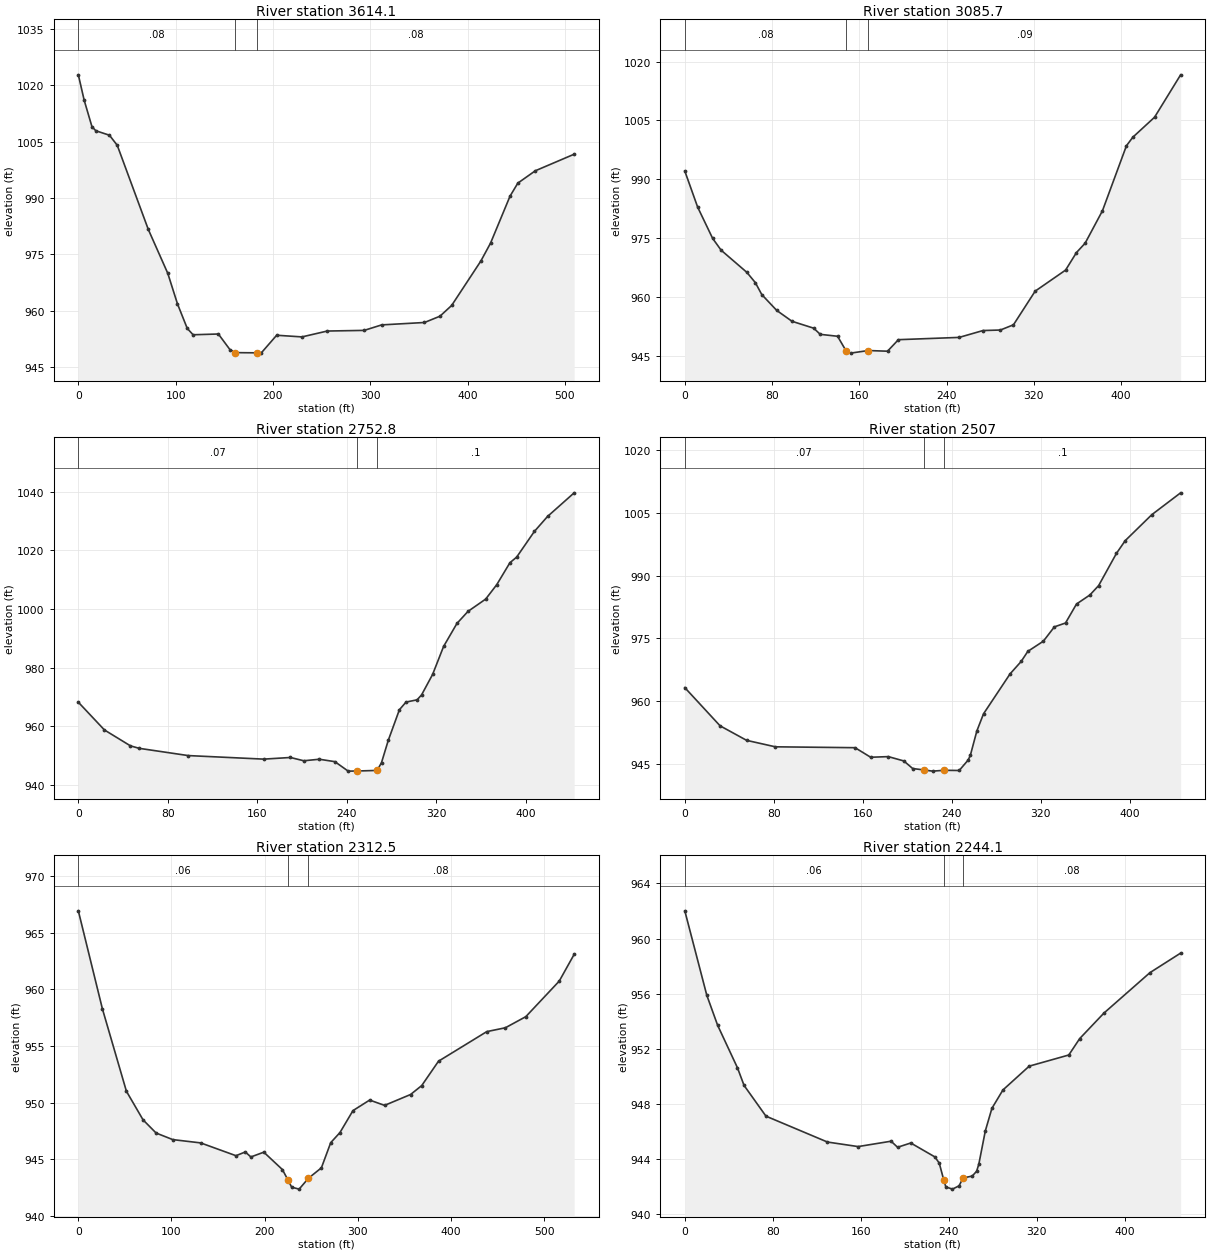
Type RM Length L Ch R = 1 ,3614.1  ,524.5,528.4,533.3
XS GIS Cut Line= 2
     1680425.142      604703.689     1680902.572      604525.738
#Sta/Elev= 30
       0 1022.72       6 1015.98      14 1008.94      18 1007.86      32 1006.67
      40 1003.99    71.9  981.64    91.9  969.99   101.9  961.85   111.9  955.36
   117.9  953.66   143.9  953.86   155.8  949.71   161.5  948.91   183.8  948.86
   187.8  948.78   203.8  953.53   229.8  953.09   255.8  954.65   293.7  954.82
   311.7  956.28   355.7  956.92   371.6  958.59   383.6  961.44   413.6  973.24
   423.6  978.02   443.6  990.48   451.6  993.94   469.6  997.23   509.5 1001.63
#Mann= 3 , 0 , 0
       0     .08       0   161.5    .045       0   183.8     .08       0
Bank Sta=161.5,183.8
XS Rating Curve= 0 ,0
Exp/Cntr=0.3,0.1

Type RM Length L Ch R = 1 ,3085.7  ,326.5,332.8,337.1
XS GIS Cut Line= 3
     1680637.815      605161.589      1680715.94      605135.547
     1681063.162      605000.998
#Sta/Elev= 30
       0  992.11    11.8   982.9    25.5  974.95    33.3  971.93    56.9  966.28
    64.7  963.65    70.6  960.61    84.3  956.57    98.3   953.8   118.2  952.04
   124.2  950.47   140.1  949.98   148.1  946.16     152  945.68   168.3  946.34
   185.9  946.17   195.9  949.11   251.6  949.69   273.5  951.44   289.4  951.57
   301.4   952.9   321.3  961.48   349.2  966.85   359.2  971.33   367.1   973.7
     383  981.97     405  998.55   410.9 1000.74   430.8 1005.83   454.7 1016.64
#Mann= 3 , 0 , 0
       0     .08       0   148.1    .045       0   168.3     .09       0
Bank Sta=148.1,168.3
XS Rating Curve= 0 ,0
Exp/Cntr=0.3,0.1

Type RM Length L Ch R = 1 ,2752.8  ,235,245.9,256
XS GIS Cut Line= 4
      1680718.11      605376.432     1680772.364      605380.773
     1681015.419      605354.731     1681154.308      605315.668
#Sta/Elev= 30
       0  968.25    23.3   958.8    46.6  953.37    54.4  952.53    98.2  950.06
   165.7  948.85   189.6  949.41   201.5  948.29   215.4  948.81   229.3  947.99
   241.2  944.76   249.4   944.8   267.1     945     271  947.66     277   955.2
     287  965.69   292.9  968.29   302.8  969.06   306.8  970.73   316.7  977.74
   326.5  987.26   338.4  995.08   348.3   999.2   364.1 1003.39     374  1008.3
   385.8  1015.8   391.8  1017.7   407.6 1026.43   419.4 1031.55   443.2 1039.61
#Mann= 3 , 0 , 0
       0     .07       0   249.4    .045       0   267.1      .1       0
Bank Sta=249.4,267.1
XS Rating Curve= 0 ,0
Exp/Cntr=0.3,0.1

Type RM Length L Ch R = 1 ,2507    ,194.8,194.4,193.8
XS GIS Cut Line= 3
     1680726.791      605519.661     1680772.364      605539.193
     1681143.457      605678.082
#Sta/Elev= 30
       0  963.26    31.7  954.15    55.6  950.68    81.4  949.14   153.1  948.93
   167.1  946.65     183   946.8   196.9  945.77   204.9  943.96   214.8  943.63
   222.8  943.34   233.4  943.54   246.7  943.49   254.7  945.96   256.7  947.07
   262.6  952.93   268.6  957.02   292.5  966.55   302.4  969.49   308.4   971.9
   322.4  974.34   332.3  977.75   342.3  978.67   352.2   983.2   364.2  985.35
   372.1   987.6   388.1  995.28     396  998.32   419.9 1004.51   445.8 1009.72
#Mann= 3 , 0 , 0
       0     .07       0   214.8    .045       0   233.4      .1       0
Bank Sta=214.8,233.4
XS Rating Curve= 0 ,0
Exp/Cntr=0.3,0.1

Type RM Length L Ch R = 1 ,2312.5  ,68.9,68.5,67.8
XS GIS Cut Line= 4
     1680668.197      605706.293      1680709.43      605725.825
     1680965.506        605814.8     1681143.457      605936.328
#Sta/Elev= 30
       0  966.92    25.8  958.28    51.6     951    69.5  948.47    83.5  947.31
   101.4  946.73   131.3  946.44   169.2  945.31   179.2  945.64   185.2   945.2
   199.1  945.62     219  944.09     225  943.17     229  942.53     237  942.36
     247  943.32   260.9  944.24   270.9  946.46   280.8  947.35   294.8  949.29
   312.7  950.22   328.7  949.75   356.6  950.71   368.6   951.5   386.6  953.65
   438.4  956.26   458.4   956.6   480.3  957.58   516.2  960.72   532.2  963.08
#Mann= 3 , 0 , 0
       0     .06       0     225    .045       0     247     .08       0
Bank Sta=225,247
XS Rating Curve= 0 ,0
Exp/Cntr=0.3,0.1

Type RM Length L Ch R = 1 ,2244.1  ,55.4,55,55.4
XS GIS Cut Line= 2
     1680637.815      605780.078     1681067.503      605916.797
#Sta/Elev= 30
       0  962.01      20  955.88    29.9  953.69    47.9  950.61    53.9  949.33
    73.8   947.1   129.7  945.22   157.6  944.89   187.6  945.28   193.5  944.84
   205.5  945.15   227.4  944.14   231.4  943.69   235.4  942.49   237.4  941.96
   243.4   941.8   249.4  942.04   253.1  942.61   261.4  942.75   265.4   943.1
   267.4  943.62   273.3  946.03   279.3  947.67   289.3     949   313.2  950.73
   349.2  951.54   359.1  952.73   381.1  954.58     423  957.52   450.9  958.94
#Mann= 3 , 0 , 0
       0     .06       0   235.4    .045       0   253.1     .08       0
Bank Sta=235.4,253.1
XS Rating Curve= 0 ,0
Exp/Cntr=0.3,0.1

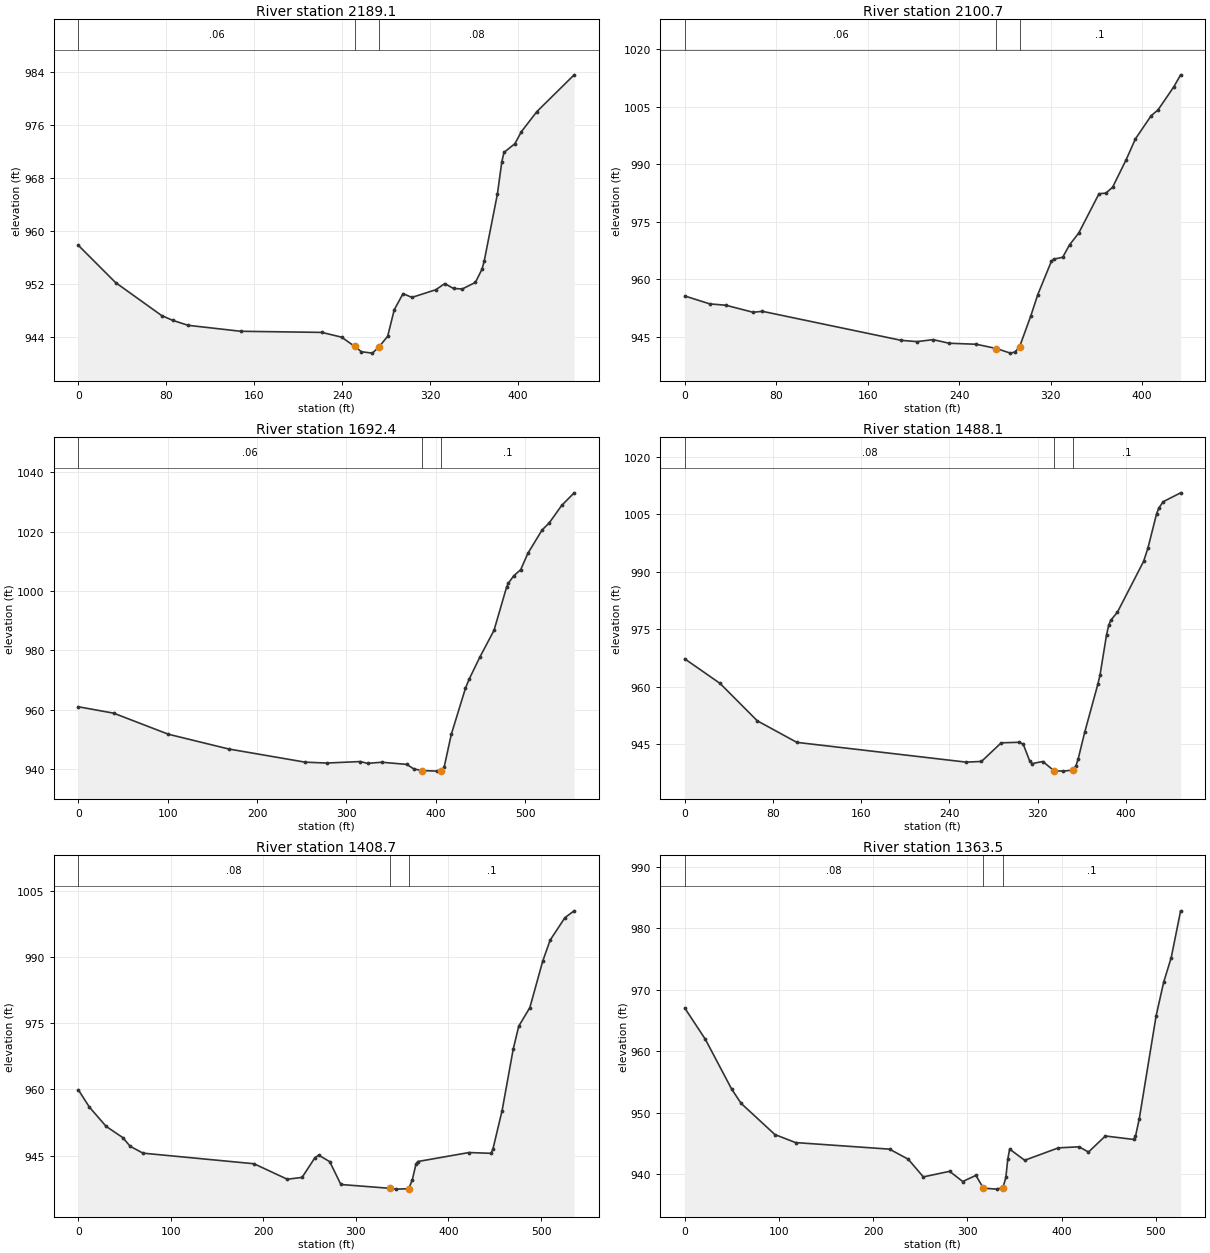
Type RM Length L Ch R = 1 ,2189.1  ,85.7,88.4,89.5
XS GIS Cut Line= 2
     1680616.114      605829.991     1681045.801       605966.71
#Sta/Elev= 30
       0  957.85    33.9  952.22    75.8  947.24    85.8  946.52    99.8  945.77
   147.6  944.87   221.5   944.7   239.4  943.98   251.4  942.58   257.4  941.78
   267.4  941.57   273.3  942.49   281.3  944.11   287.3  948.12   295.3  950.56
   303.3  949.98   325.2  951.15   333.2  952.07   341.2  951.33   349.2  951.26
   361.1  952.25   367.1  954.25   369.1  955.47   381.1  965.59   385.1  970.45
   387.1  971.88     397  973.19     403  975.03     417  978.04   450.9  983.59
#Mann= 3 , 0 , 0
       0     .06       0   251.4    .045       0   273.3     .08       0
Bank Sta=251.4,273.3
XS Rating Curve= 0 ,0
Exp/Cntr=0.3,0.1

Type RM Length L Ch R = 1 ,2100.7  ,389.1,408.3,426.2
XS GIS Cut Line= 4
     1680598.753      605886.415     1680700.749      605931.988
     1680904.742      606016.623     1680987.207      606075.217
#Sta/Elev= 30
       0  955.64    21.9  953.58    35.9  953.23    59.8  951.39    67.8  951.65
   189.3  944.08   203.2  943.75   217.2  944.27   231.1  943.33     255  943.06
   272.6  941.95   284.8  940.75   288.8  941.05   292.8  942.39   302.7  950.49
   308.7  955.96   320.6  964.65   322.6  965.22   330.6  965.74   336.5  968.96
   344.5     972   362.3  982.28   368.3  982.45   374.2  983.98   386.1  991.18
   394.1  996.55   407.9 1002.61   413.9 1004.12   427.8 1010.17   433.7 1013.27
#Mann= 3 , 0 , 0
       0     .06       0   272.6    .045       0   292.8      .1       0
Bank Sta=272.6,292.8
XS Rating Curve= 0 ,0
Exp/Cntr=0.3,0.1

Type RM Length L Ch R = 1 ,1692.4  ,205.8,204.2,202.2
XS GIS Cut Line= 3
     1680483.735      605931.988     1680507.607      606062.196
     1680657.346      606457.161
#Sta/Elev= 30
       0  960.97    39.5  958.81   100.8   951.7   168.2  946.73   253.9  942.28
   277.8  941.99   315.7  942.49   323.6  941.88   339.6  942.26   367.5  941.53
   375.5  939.99   384.6  939.46   401.4  939.26   405.3  939.32   407.3  939.42
   409.3  940.55   417.3  951.64   433.2  967.25   437.2  970.21   449.2  977.68
   465.1  986.73   479.1 1001.22   481.1 1002.62     487 1005.06     495 1007.23
     503 1012.71   518.9  1020.6   526.9 1022.98   540.8 1028.86   554.8 1033.13
#Mann= 3 , 0 , 0
       0     .06       0   384.6    .045       0   405.3      .1       0
Bank Sta=384.6,405.3
XS Rating Curve= 0 ,0
Exp/Cntr=0.3,0.1

Type RM Length L Ch R = 1 ,1488.1  ,24.6,79.4,112.1
XS GIS Cut Line= 3
     1680268.457      606074.421     1680423.839      606408.623
     1680430.784      606489.352
#Sta/Elev= 30
       0  967.26    31.9  960.88    65.7  951.12   101.6  945.49     255  940.34
     269  940.51   286.9  945.37   302.8  945.51   306.8  945.07   312.8   940.6
   314.8  939.95   324.7   940.5   334.7  938.11   342.7  937.99   351.6  938.24
   354.6  939.32   356.6  941.05   362.6   948.1   374.5  960.61   376.5  963.04
   382.4  973.48   384.4  976.05   386.3  977.34   392.3  979.45     416  992.67
   419.9  996.09   427.8 1005.09   429.8 1006.58   433.8 1008.25   449.6 1010.56
#Mann= 3 , 0 , 0
       0     .08       0   334.7    .045       0   351.6      .1       0
Bank Sta=334.7,351.6
XS Rating Curve= 0 ,0
Exp/Cntr=0.3,0.1

Type RM Length L Ch R = 1 ,1408.7  ,66.6,45.2,53.2
XS GIS Cut Line= 4
     1680241.548      606123.032      1680383.24      606378.024
     1680255.437      606460.706     1680302.312      606539.699
#Sta/Elev= 30
       0  959.88      12  955.96      30  951.61      48  949.07      56   947.1
    69.9  945.54   189.8  943.14   225.8  939.63   241.8  940.05   255.8  944.55
   259.8  945.08   271.7  943.61   283.7  938.44   336.8  937.57   343.1  937.39
     357  937.48   360.9  939.51   364.9  943.09   366.8  943.64   422.2  945.68
   445.9   945.5   447.9  946.37   457.9  955.15   469.9  969.05   475.9   974.3
   487.9   978.5   501.8  989.01   509.8  993.77   525.8  998.88   535.8 1000.43
#Mann= 3 , 0 , 0
       0     .08       0   336.8    .045       0     357      .1       0
Bank Sta=336.8,357
XS Rating Curve= 0 ,0
Exp/Cntr=0.3,0.1

Type RM Length L Ch R = 1 ,1363.5  ,175.5,139.8,94.2
XS GIS Cut Line= 4
     1680202.485      606105.671     1680337.902      606356.539
     1680216.374      606443.345     1680263.249      606522.338
#Sta/Elev= 30
       0  967.02    21.9  961.91    49.8  953.81    59.8   951.5    95.7  946.42
   117.6  945.12   217.3  944.05   237.2  942.41   253.2  939.53   281.1  940.44
     295  938.78     309  939.78   316.9   937.7   330.9  937.54   337.7  937.79
   340.8  939.44   342.8  942.39   344.8  944.05   360.8  942.24   396.6  944.26
   418.5  944.43   428.5  943.58   446.4  946.19   476.4  945.63   478.4  946.15
   482.4  948.99   500.3  965.76   508.3  971.23   516.3  975.22   526.3  982.85
#Mann= 3 , 0 , 0
       0     .08       0   316.9    .045       0   337.7      .1       0
Bank Sta=316.9,337.7
XS Rating Curve= 0 ,0
Exp/Cntr=0.3,0.1