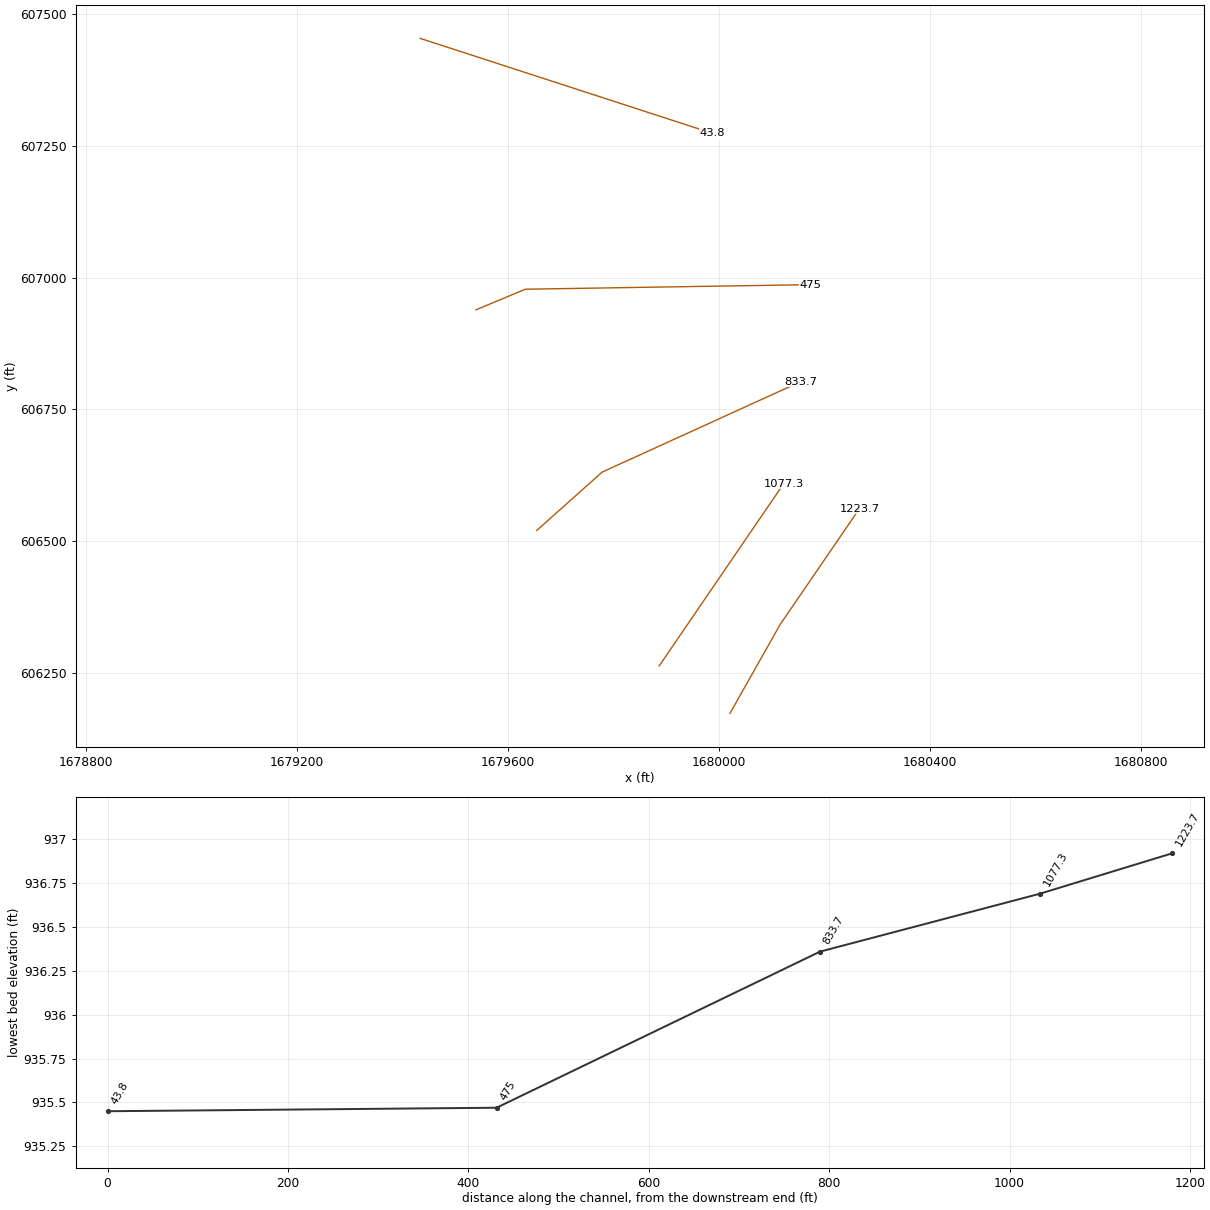
HEC-RAS study CSTLMNRN.prj: CSTLMNRN

--- CSTLMNRN.g01 (geometry) --- (continued)

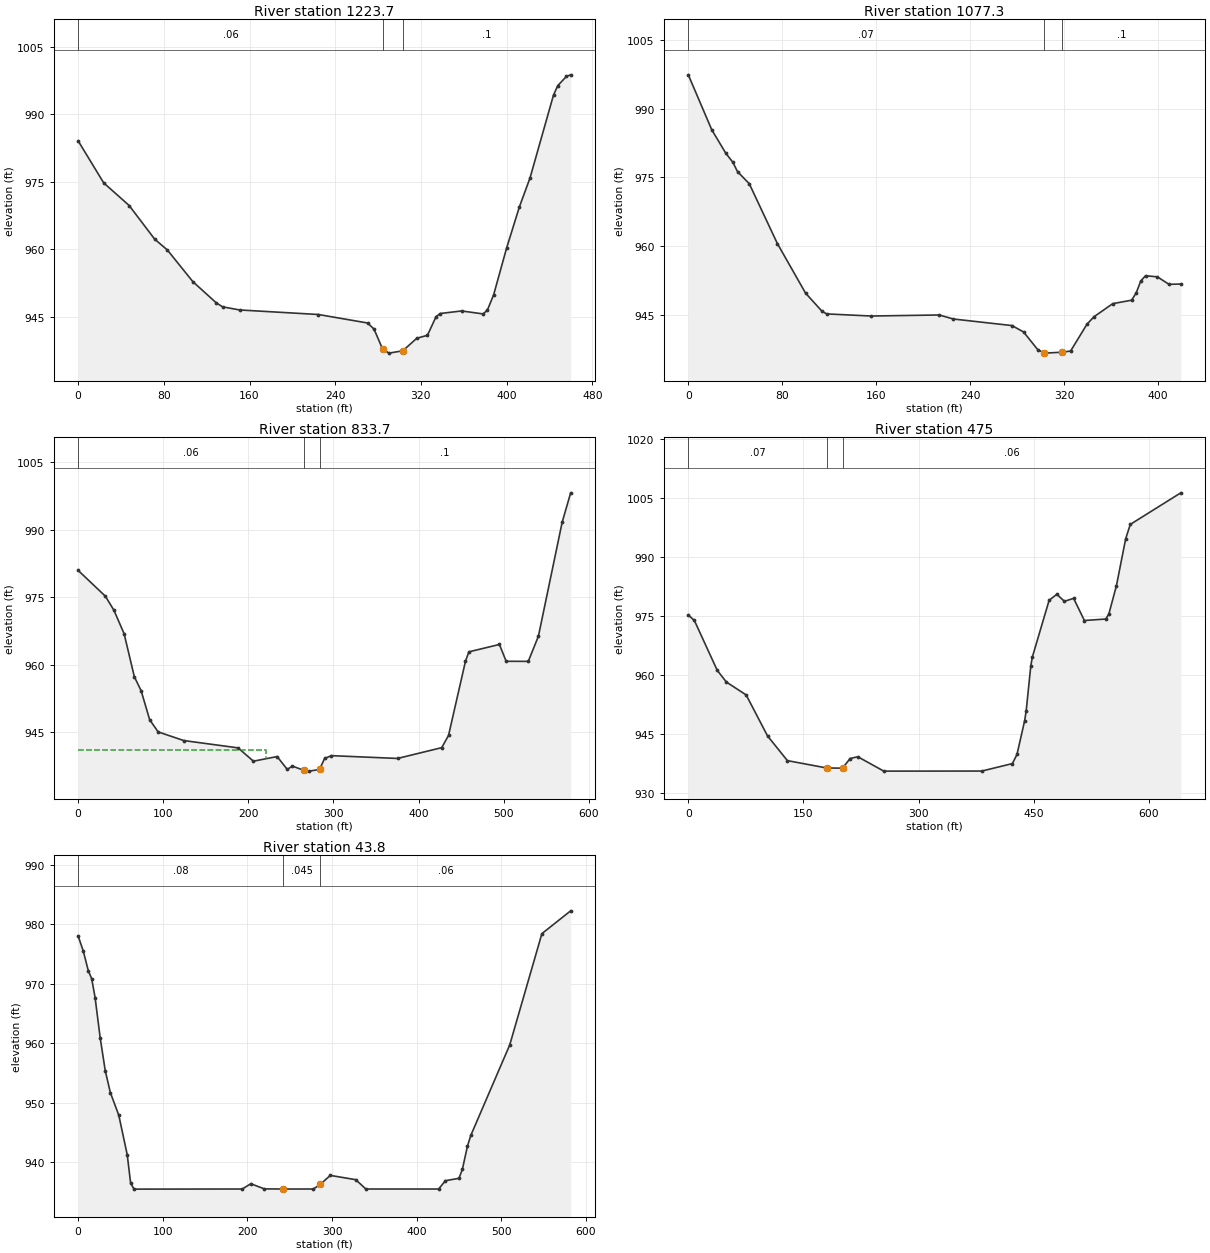
Type RM Length L Ch R = 1 ,1223.7  ,145.8,146.4,145.9
XS GIS Cut Line= 3
     1680020.628      606172.873     1680116.114      606342.144
     1680265.853      606561.328
#Sta/Elev= 30
       0  984.12    23.8  974.79    47.6  969.75    71.4  962.28    83.3  959.85
   107.1  952.81   128.9  948.11   134.8  947.22   150.7  946.52   224.3  945.51
   270.2  943.62   276.2  942.27   284.2  937.83   290.2  936.92   303.1  937.44
   316.1  940.22   326.1  940.89   334.1  945.01     338  945.73     358   946.3
     378  945.64     382  946.46   387.9  949.89   399.9  960.21   411.9  969.42
   421.9  975.91   443.8  994.33   447.8  996.41   455.8  998.45   459.8  998.81
#Mann= 3 , 0 , 0
       0     .06       0   284.2    .045       0   303.1      .1       0
Bank Sta=284.2,303.1
XS Rating Curve= 0 ,0
Exp/Cntr=0.3,0.1

Type RM Length L Ch R = 1 ,1077.3  ,257.8,243.7,229.4
XS GIS Cut Line= 2
     1679886.513      606262.789     1680122.624      606609.144
#Sta/Elev= 30
       0  997.37      20  985.37    31.9  980.29    37.9  978.31    41.9  976.26
    51.9  973.63    75.8  960.59    99.8  949.78   113.8  945.82   117.8  945.24
   155.7  944.78   213.6  945.01   225.6  944.13   275.5   942.7   285.4   941.3
   297.4  937.46   302.9  936.71   303.4  936.69   317.9  936.89   325.4  937.14
   339.3  942.98   345.3  944.62   361.3  947.48   377.3  948.23   381.2  949.79
   385.2  952.45   389.2  953.56   399.2  953.33   409.2  951.69   419.2  951.76
#Mann= 3 , 0 , 0
       0     .07       0   302.9    .045       0   317.9      .1       0
Bank Sta=302.9,317.9
XS Rating Curve= 0 ,0
Exp/Cntr=0.3,0.1

Type RM Length L Ch R = 1 ,833.7   ,367.6,358.6,344.3
XS GIS Cut Line= 3
     1679654.742      606520.096      1679778.44      606630.773
     1680153.874      606802.214
#Sta/Elev= 30
       0  980.98      32  975.24      42  972.13      54   966.9      66  957.35
      74  954.23      84  947.79      94  945.08     124  943.16   187.9  941.53
   205.9  938.57   233.8   939.6   245.7  936.74   251.7  937.48   265.6   936.5
   271.7  936.36   283.6  936.73   289.6  939.18   297.6   939.8   375.3  939.18
   427.2  941.58   435.2   944.3   455.1  960.79   459.1  962.88     495  964.52
   502.9  960.78   528.9  960.76   540.8  966.35   568.7  991.68   578.7  998.23
#Mann= 3 , 0 , 0
       0     .06       0   265.6    .045       0   283.6      .1       0
#XS Ineff= 2 , 0
       0  220.95  941.05               0
Permanent Ineff=
       F       F
Bank Sta=265.6,283.6
XS Rating Curve= 0 ,0
Exp/Cntr=0.3,0.1

Type RM Length L Ch R = 1 ,475     ,444.6,431.3,426.1
XS GIS Cut Line= 3
     1679539.725      606938.932     1679633.041      606977.995
     1680173.405      606986.675
#Sta/Elev= 30
       0  975.17     7.9  973.77    37.7   961.1    49.6  958.12    75.4  954.84
   103.2  944.43   129.1  938.14   180.1  936.28   200.9  936.22   210.8  938.67
   220.8  939.13   254.7  935.47   382.4  935.49   422.2  937.39   428.2  939.71
   438.2   948.3   440.2  950.81   446.2  962.22   448.2  964.46   470.1  978.91
   480.1  980.43     490  978.64     502  979.39     516  973.76   543.9  974.14
   547.9  975.42   557.8  982.65   569.8  994.54   575.8  998.19   641.6 1006.22
#Mann= 3 , 0 , 0
       0     .07       0   180.1    .045       0   200.9     .06       0
Bank Sta=180.1,200.9
XS Rating Curve= 0 ,0
Exp/Cntr=0.3,0.1

Type RM Length L Ch R = 1 ,43.8    ,11.4,43.8,68.5
XS GIS Cut Line= 2
     1679433.631      607454.193     1679987.016      607274.071
#Sta/Elev= 30
       0  978.04       6  975.54      12   972.2      16  970.85      20   967.7
      26  960.93      32  955.39      38  951.71      48  947.89      58  941.22
      62  936.46      66  935.45     194  935.47     204  936.36     220  935.49
     242  935.47     278  935.47     286  936.24     298  937.76     328  937.04
     340  935.47     426  935.47     434  936.87     450  937.27     454  938.76
     460  942.67     464  944.49     510  959.72     548  978.45     582  982.29
#Mann= 3 , 0 , 0
       0     .08       0     242    .045       0     286     .06       0
Bank Sta=242,286
XS Rating Curve= 0 ,0
Exp/Cntr=0.3,0.1

Chan Stop Cuts=-1
Use User Specified Reach Order=0
Composite Channel Slope=5